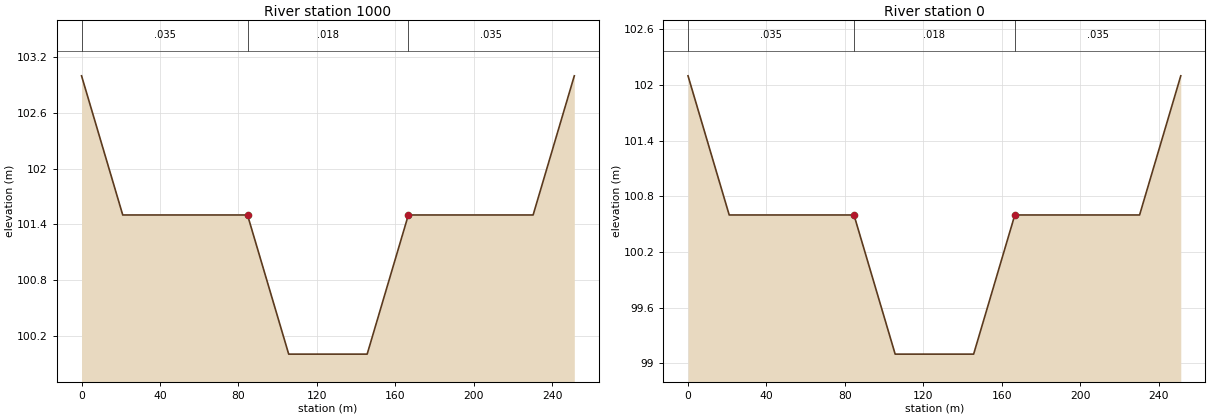
--- HECRASProtCanal_v.prj (project) ---

Proj Title=CanalPrincipalCompuestoPrototipo
Current Plan=p01
Default Exp/Contr=0.3,0.1
SI Units
Geom File=g01
Flow File=f01
Flow File=f02
Unsteady File=u01
Plan File=p02
Plan File=p01
Y Axis Title=Elevation
X Axis Title(PF)=Main Channel Distance
X Axis Title(XS)=Station
BEGIN DESCRIPTION:
HCMC - Herramientas computacionales para el diseño y modelación de cauces.
1.13. Diseño geométrico e hidráulico vertical del cauce principal de desviación y cauces laterales menores.
Prototipo canal cumpuesto cauce principal.
Contenido creado por:
William Ricardo Aguilar Piña
william.aguilar@escuelaing.edu.co
r.cfdtools@gmail.com
Profesor Asistente, Ingeniero Civil., Programador, Diseñador y Analista de Sistemas, Especialista en Recursos Hidráulicos y Medio Ambiente, Máster en Desarrollo Urbano y Territorial
Escuela Colombiana de Ingeniería Julio Garavito
www.escuelaing.edu.co
Micrositio
https://bit.ly/36igDyV
Licencia, cláusulas y condiciones de uso en:
https://bit.ly/2LAOE3M
END DESCRIPTION:
DSS File=dss
DSS Export Rating Curves= 0
DSS Export Rating Curve Sorted= 0
DSS Export Volume Flow Curves= 0
DXF OffsetX= 0
DXF OffsetY= 0
DXF ScaleX= 1
DXF ScaleY= 10

--- HECRASProtCanal_v.p01 (plan) ---

Plan Title=Unsteady
Program Version=5.07
Short Identifier=Unsteady
Simulation Date=01SEP2008,0015,02SEP2008,0015
Geom File=g01
Flow File=u01
Subcritical Flow
K Sum by GR= 0
Std Step Tol= 0.003
Critical Tol= 0.003
Num of Std Step Trials= 20
Max Error Tol= 0.1
Flow Tol Ratio= 0.001
Split Flow NTrial= 30
Split Flow Tol= 0.006
Split Flow Ratio= 0.02
Log Output Level= 0
Friction Slope Method= 1
Unsteady Friction Slope Method= 2
Unsteady Bridges Friction Slope Method= 1
Calc Critical at every XS
Parabolic Critical Depth
Global Vel Dist= 0 , 0 , 0
Global Log Level= 0
CheckData=True
Encroach Param=-1 ,0,0, 0
Computation Interval=1MIN
Output Interval=15MIN
Instantaneous Interval=15MIN
Mapping Interval=15MIN
Computation Time Step Use Courant=        0
Computation Time Step Use Time Series=    0
Computation Time Step Count To Double=0
Computation Time Step Max Doubling=0
Computation Time Step Max Halving=0
Computation Time Step Residence Courant=0
Run HTab=-1
Run UNet=-1
Run Sediment= 0
Run PostProcess=-1
Run WQNet= 0
Run RASMapper= 0
UNET Theta= 1
UNET Theta Warmup= 1
UNET ZTol= 0.006
UNET ZSATol= 0.006
UNET MxIter= 20
UNET Max Iter WO Improvement= 0
UNET MaxInSteps= 0
UNET DtIC= 0
UNET DtMin= 0
UNET MaxCRTS= 20
UNET WFStab= 2
UNET SFStab= 1
UNET WFX= 1
UNET SFX= 1
UNET 1D Methodology=Finite Difference
UNET DSS MLevel= 4
UNET Pardiso=0
UNET DZMax Abort= 30
UNET Use Existing IB Tables=-1
UNET Froude Reduction=False
UNET Froude Limit= 0.8
UNET Froude Power= 4
UNET D1 Cores= 0
UNET D2 Coriolis=0
UNET D2 Cores= 0
UNET D2 Theta= 1
UNET D2 Theta Warmup= 1
UNET D2 Z Tol= 0.003
UNET D2 Volume Tol= 0.003
UNET D2 Max Iterations= 20
UNET D2 Equation= 0
UNET D2 RampUpFraction=0.1
UNET D2 TimeSlices= 1
UNET D2 BCVolumeCheck=0
UNET D1D2 MaxIter= 0
UNET D1D2 ZTol=0.003
UNET D1D2 QTol=0.1
UNET D1D2 MinQTol=0.03
DSS File=dss
Write IC File= 0
Write IC File at Fixed DateTime=0
Write IC File at Sim End=0
Echo Input=False
Echo Parameters=False
Echo Output=False
Write Detailed= 0
HDF Write Warmup=0
HDF Write Time Slices=0
HDF Flush=0
HDF Face Node Velocities=0
HDF Compression= 1
HDF Chunk Size= 1
HDF Spatial Parts= 1
HDF Use Max Rows=0
HDF Fixed Rows= 1
Calibration Method= 0
Calibration Iterations= 20
Calibration Max Change=0.05
Calibration Tolerance=0.2
Calibration Maximum=1.5
Calibration Minimum=0.5
Calibration Optimization Method= 1
WQ AD Non Conservative
WQ ULTIMATE=-1
WQ Max Comp Step=1HOUR
WQ Output Interval=15MIN
WQ Output Selected Increments= 0
WQ Output face flow=0
WQ Output face velocity=0
WQ Output face area=0
WQ Output face dispersion=0
WQ Output cell volume=0
WQ Output cell surface area=0
WQ Output cell continuity=0
WQ Output cumulative cell continuity=0
WQ Output face conc=0
WQ Output face dconc_dx=0
WQ Output face courant=0
WQ Output face peclet=0
WQ Output face adv mass=0
WQ Output face disp mass=0
WQ Output cell mass=0
WQ Output cell source sink temp=0
WQ Output nsm pathways=0
WQ Output nsm derived pathways=0
WQ Output MaxMinRange=-1
WQ Daily Max Min Mean=-1
WQ Daily Range=0
WQ Daily Time=0
WQ Create Restart=0
WQ Fixed Restart=0
WQ System Summary=0
WQ Write To DSS=0
WQ Use Fixed Temperature=0
Sorting and Armoring Iterations= 10
XS Update Threshold= 0.02
Bed Roughness Predictor= 0
Hydraulics Update Threshold= 0.02
Energy Slope Method= 1
Volume Change Method= 1
Sediment Retention Method= 0
XS Weighting Method= 0
Number of US Weighted Cross Sections= 1
Number of DS Weighted Cross Sections= 1
Upstream XS Weight=0
Main XS Weight=1
Downstream XS Weight=0
Number of DS XS's Weighted with US Boundary= 1
Upstream Boundary Weight= 1
Weight of XSs Associated with US Boundary= 0
Number of US XS's Weighted with DS Boundary= 1
Downstream Boundary Weight= 0.5
Weight of XSs Associated with DS Boundary= 0.5
Percentile Method= 0
Sediment Output Level= 3
Mass or Volume Output= 0
Output Increment Type= 1
Profile and TS Output Increment= 1
XS Output Flag= 0
XS Output Increment= 10
Write Gradation File= 0
Read Gradation Hotstart= 0
Write HDF5 File= 1
Write Binary Output= 1
Write DSS Sediment File= 0
SV Curve= 0
Specific Gage Flag= 0

--- HECRASProtCanal_v.p02 (plan) ---

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Plan Title=Steady
Geom File=g01
Flow File=f01
Output Interval=1HOUR
Instantaneous Interval=1HOUR
Mapping Interval=1HOUR
Run HTab= 0
Run UNet= 0
Run PostProcess= 0

--- HECRASProtCanal_v.f01 (steady flow) ---

Flow Title=Steady
Program Version=5.07
Number of Profiles= 7
Profile Names=Tr2.33yr,Tr5yr,Tr10yr,Tr25yr,Tr50yr,Tr100yr,Qm
River Rch & RM=CanalPrincipal,CanalPrincipal  ,1000
     130   205.9   275.3   369.9     445   522.1    1.92
Boundary for River Rch & Prof#=CanalPrincipal,CanalPrincipal  , 1
Up Type= 0
Dn Type= 3
Dn Slope=0.000897
DSS Import GetInterval= 0
DSS Import GetPeak= 0
DSS Import FillOption= 0

--- HECRASProtCanal_v.f02 (steady flow) ---

Flow Title=Flow 02
Program Version=5.07
Number of Profiles= 1
Profile Names=PF 1
DSS Import GetInterval= 0
DSS Import GetPeak= 0
DSS Import FillOption= 0

--- HECRASProtCanal_v.u01 (unsteady flow) ---

Flow Title=Unsteady
Program Version=5.07
Use Restart= 0
Initial Flow Loc=CanalPrincipal  ,CanalPrincipal  ,1000    ,0.0001
Keep SA Constant=-1
Boundary Location=CanalPrincipal  ,CanalPrincipal  ,1000    ,        ,                ,                ,                ,
Interval=1MIN
Flow Hydrograph= 4321
       0       0       0       0       0       0       0       0       0       0
       0       0       0       0       0       0       0       0       0       0
       0       0       0       0      .1      .1      .1      .1      .1      .1
      .1      .2      .2      .2      .3      .3      .3      .4      .4      .5
      .5      .6      .6      .7      .7      .8      .9       1     1.1     1.1
     1.2     1.3     1.4     1.5     1.7     1.8     1.9       2     2.2     2.3
     2.5     2.6     2.8     2.9     3.1     3.3     3.5     3.7     3.9     4.1
     4.3     4.5     4.7       5     5.2     5.4     5.7       6     6.2     6.5
     6.8     7.1     7.4     7.7       8     8.3     8.6     8.9     9.2     9.6
     9.9    10.3    10.6      11    11.4    11.7    12.1    12.5    12.9    13.3
    13.7    14.1    14.5    14.9    15.3    15.8    16.2    16.7    17.1    17.6
      18    18.5    18.9    19.4    19.9    20.4    20.9    21.4    21.8    22.4
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Use DSS=False
Use Fixed Start Time=False
Is Critical Boundary=False
Boundary Location=CanalPrincipal  ,CanalPrincipal  ,0       ,        ,                ,                ,                ,
Friction Slope=0.000897,0

--- HECRASProtCanal_v.g01 (geometry) ---

Geom Title=CanalPrincipalCompuesto
Program Version=5.07

River Reach=CanalPrincipal  ,CanalPrincipal
Reach XY= 2
        1001000.        1000000.        1000000.        1000000.

Type RM Length L Ch R = 1 ,1000    ,100,100,100
BEGIN DESCRIPTION:
Sección de inicio aguas arriba.
END DESCRIPTION:
#Sta/Elev= 8
       0     103      21   101.5    84.6   101.5   105.6     100   145.6     100
   166.6   101.5   230.2   101.5   251.2     103
#Mann= 3 , 0 , 0
       0    .035       0    84.6    .018       0   166.6    .035       0
Bank Sta=84.6,166.6
XS Rating Curve= 0 ,0
Exp/Cntr=0.3,0.1

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
Type RM Length L Ch R = 1 ,0       ,1000,1000,1000
BEGIN DESCRIPTION:
Sección de entrega aguas abajo.
END DESCRIPTION:
#Sta/Elev= 8
       0   102.1      21   100.6    84.6   100.6   105.6    99.1   145.6    99.1
   166.6   100.6   230.2   100.6   251.2   102.1
#Mann= 3 , 0 , 0
       0    .035       0    84.6    .018       0   166.6    .035       0
Bank Sta=84.6,166.6
XS Rating Curve= 0 ,0
Exp/Cntr=0.3,0.1
LCMann Table=0

Chan Stop Cuts=-1
Use User Specified Reach Order=0
Composite Channel Slope=5